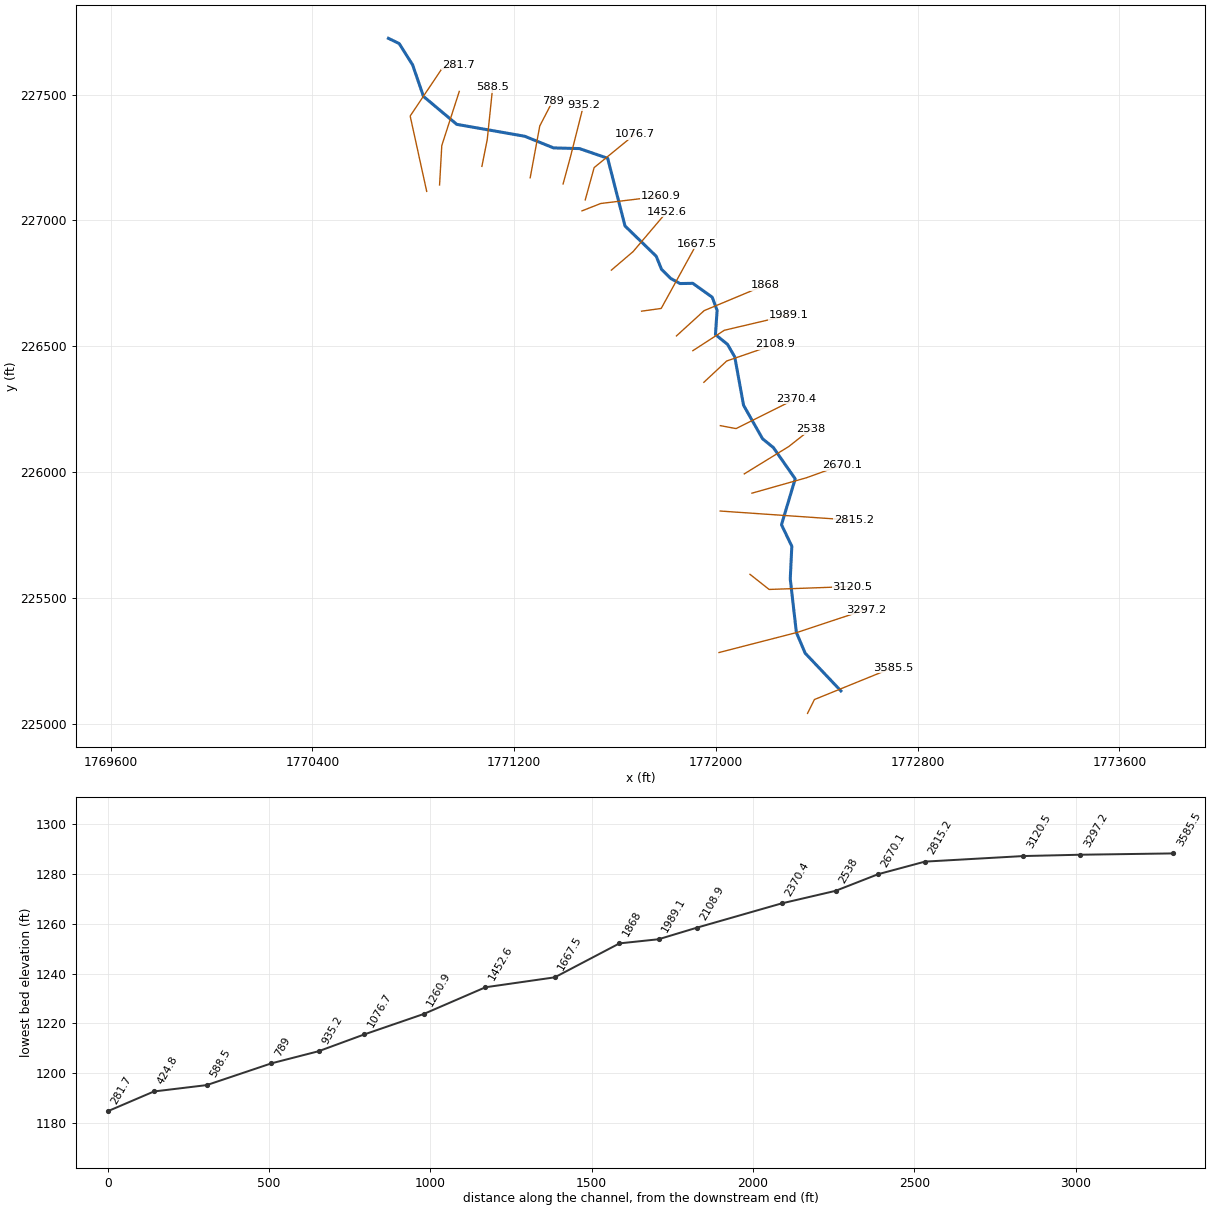
--- SchlhousBr.prj (project) ---

Proj Title=SchlhousBr
Current Plan=p01
Default Exp/Contr=0,0
English Units
Geom File=g01
Flow File=f01
Plan File=p01
BEGIN DESCRIPTION:
END DESCRIPTION:
DSS Export Rating Curves= 0
DSS Export Rating Curve Sorted= 0
DSS Export Volume Flow Curves= 0
DXF OffsetX= 0
DXF OffsetY= 0
DXF ScaleX= 0
DXF ScaleY= 0

--- SchlhousBr.p01 (plan) ---

Plan Title=Floodplain
Program Version=4.00
Geom File=g01
Flow File=f01
K Sum by GR=0
Std Step Tol=0.01
Critical Tol=0.01
Num of Std Step Trials=20
Max Error Tol=0.3
Flow Tol Ratio=0.001
Split Flow NTrial=30
Split Flow Tol=0.02
Split Flow Ratio=0.02
Log Output Level=0
Friction Slope Method=1
Unsteady Friction Slope Method=2
Unsteady Bridges Friction Slope Method=1
Global Log Level=0
CheckData=False
Run HTab=0
Run UNet=0
Run PostProcess=0
UNET Theta=0
UNET Theta Warmup=0
UNET ZTol=0
UNET ZSATol=0
UNET MxIter=0
UNET MaxInSteps=0
UNET DtIC=0
UNET DtMin=0
UNET MaxCRTS=0
UNET WFStab=0
UNET SFStab=0
UNET WFX=0
UNET SFX=0
UNET DSS MLevel=0
UNET DZMax Abort=0
UNET Convert EG Bridges=0
UNET Use Existing IB Tables=0
UNET Froude Limit=0
UNET Froude Power=0
Write IC File=0
Echo Input=False
Echo Output=False
Write Detailed=0

--- SchlhousBr.f01 (steady flow) ---

Flow Title=NFF Regression Equation
Program Version=4.00
Number of Profiles=1
Profile Names=P100yr
River Rch & RM=SchlhousBr,Main      ,3585.5
595.4563
River Rch & RM=SchlhousBr,Main      ,3297.2
599.3759
River Rch & RM=SchlhousBr,Main      ,1989.1
653.5276
River Rch & RM=SchlhousBr,Main      ,1667.5
1075.226
Boundary for River Rch & Prof#=SchlhousBr,Main      ,1
Up Type=0
Dn Type=3
Dn Slope=0.038437

--- SchlhousBr.g01 (geometry) ---

Geom Title=USGS 10m DEM
Program Version=4.00

River Reach=SchlhousBr      ,Main
Reach XY= 30
     1772495.606      225130.372     1772353.864       225280.37
     1772319.049       225362.78     1772294.811      225575.193
     1772300.981      225705.198     1772259.996      225790.692
     1772314.398      225973.056     1772227.786      226097.287
     1772184.917      226132.282     1772109.679      226265.262
     1772074.684      226457.733     1772045.813      226507.601
     1771998.183       226546.11     1772004.694      226642.331
     1771985.447      226694.823     1771908.459      226749.939
     1771857.717      226749.064     1771820.972      226769.186
     1771784.228      226805.931     1771763.231      226857.548
     1771639.501      226977.918      1771570.76      227246.864
     1771458.777      227285.358     1771356.417      227287.983
     1771241.809      227334.351      1770972.35      227381.594
     1770840.245      227492.703     1770797.376      227617.809
     1770744.009      227702.671     1770701.377      227723.447

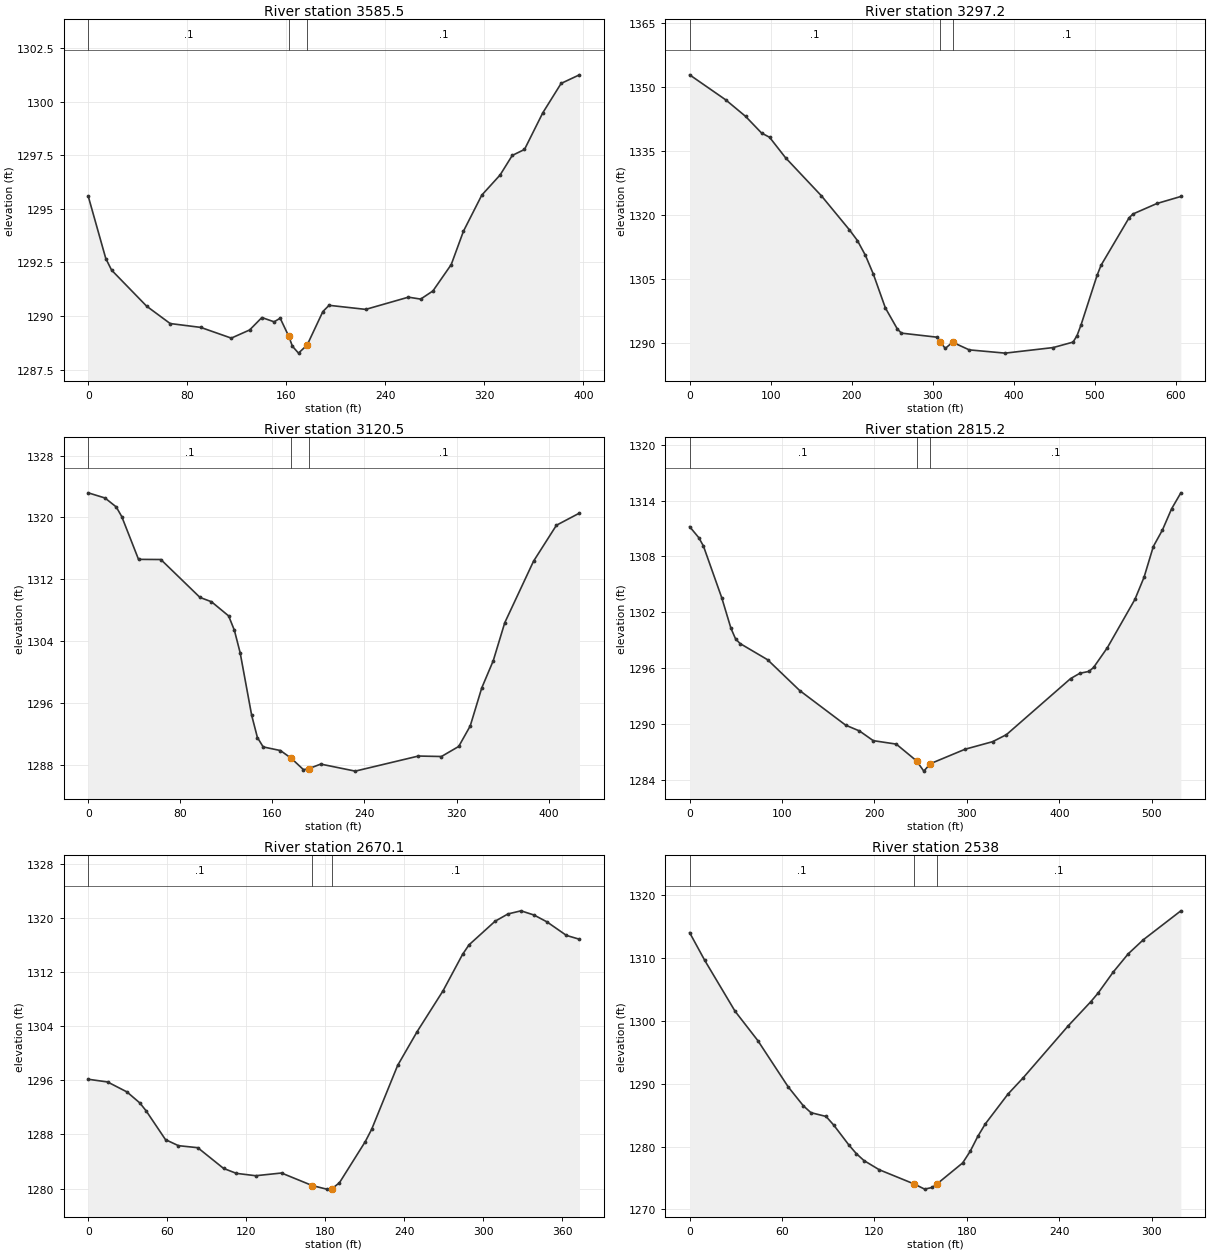
Type RM Length L Ch R = 1 ,3585.5  ,291.2,288.3,286.6
XS GIS Cut Line= 3
     1772363.373      225041.069     1772390.539      225096.041
     1772701.333      225222.704
#Sta/Elev= 30
       0 1295.59    14.2 1292.68    18.9 1292.14    47.2 1290.46    66.2 1289.65
    90.9 1289.47   115.6 1288.97   130.4 1289.35   140.3 1289.93   150.2 1289.73
   155.1  1289.9   161.9 1289.07     165 1288.59   169.9 1288.27   176.9 1288.65
   189.6 1290.21   194.6  1290.5   224.2 1290.31   258.7 1290.88   268.6 1290.79
   278.5 1291.17   293.3  1292.4   303.2 1293.96     318 1295.64   332.8 1296.58
   342.6 1297.49   352.5 1297.77   367.3 1299.48   382.1 1300.85   396.9 1301.25
#Mann= 3 , 0 , 0
       0      .1       0   161.9    .045       0   176.9      .1       0
Bank Sta=161.9,176.9
XS Rating Curve= 0 ,0
Exp/Cntr=0.3,0.1

Type RM Length L Ch R = 1 ,3297.2  ,181.6,176.7,170.5
XS GIS Cut Line= 3
     1772012.188      225282.802     1772322.679      225362.915
     1772594.066       225453.14
#Sta/Elev= 30
       0 1352.85    44.4 1347.02    69.1 1343.13    88.8 1339.24    98.7 1338.24
   118.4 1333.46   162.8 1324.53   197.3 1316.59   207.2 1314.08   217.1 1310.61
   226.9 1306.21   241.7 1298.32   256.5 1293.39   261.5 1292.42   305.9 1291.46
   309.7 1290.29   315.7 1288.84   324.7 1290.29   345.3  1288.5   389.7 1287.74
   448.9 1289.04   473.5 1290.32   478.4 1291.84   483.4 1294.38   503.1 1305.91
     508 1308.28   542.6 1319.38   547.5  1320.3   577.1 1322.75   606.6 1324.39
#Mann= 3 , 0 , 0
       0      .1       0   309.7    .045       0   324.7      .1       0
Bank Sta=309.7,324.7
XS Rating Curve= 0 ,0
Exp/Cntr=0.3,0.1

Type RM Length L Ch R = 1 ,3120.5  ,307.7,305.3,303
XS GIS Cut Line= 3
     1772134.956      225593.701     1772211.099      225533.499
     1772540.658      225545.227
#Sta/Elev= 30
       0 1323.18    14.6 1322.51    24.3 1321.36    29.1 1320.12    43.7 1314.58
    63.1 1314.56    97.1 1309.66   107.1  1309.1     122 1307.27     127 1305.41
     132 1302.51     142 1294.43     147 1291.55     152 1290.34     167 1289.87
   176.5 1288.86     187  1287.4   191.5 1287.52     202 1288.12     232 1287.21
   286.9 1289.16   306.9  1289.1   321.9  1290.4   331.9 1293.05   341.9 1297.96
   351.9 1301.48   361.9 1306.39   386.9 1314.34   406.8 1318.99   426.8 1320.56
#Mann= 3 , 0 , 0
       0      .1       0   176.5    .045       0   191.5      .1       0
Bank Sta=176.5,191.5
XS Rating Curve= 0 ,0
Exp/Cntr=0.3,0.1

Type RM Length L Ch R = 1 ,2815.2  ,136.8,145.1,153.4
XS GIS Cut Line= 2
      1772016.98      225845.121     1772547.264      225808.414
#Sta/Elev= 30
       0  1311.2     9.9 1310.02    14.9 1309.13    34.8 1303.56    44.7  1300.3
    49.7 1299.16    54.6 1298.66    84.4 1296.92   119.2 1293.61   168.9  1289.9
   183.8 1289.28   198.7 1288.24   223.6 1287.87   245.6 1286.07   253.4 1284.97
   260.6 1285.77   298.1 1287.32   327.9 1288.13   342.8 1288.88   412.3  1294.9
   422.3 1295.47   432.2 1295.67   437.2  1296.1   452.1 1298.22   481.9  1303.4
   491.8 1305.78   501.8 1309.07   511.7 1310.85   521.6 1313.12   531.6 1314.83
#Mann= 3 , 0 , 0
       0      .1       0   245.6    .045       0   260.6      .1       0
Bank Sta=245.6,260.6
XS Rating Curve= 0 ,0
Exp/Cntr=0.3,0.1

Type RM Length L Ch R = 1 ,2670.1  ,125.4,132,138.6
XS GIS Cut Line= 3
     1772142.969      225916.063     1772359.509      225977.494
     1772498.685      226027.841
#Sta/Elev= 30
       0 1296.15    14.7 1295.75    29.4 1294.28    39.2 1292.65      44 1291.48
    58.7 1287.23    68.5 1286.34    83.2 1286.04   102.8 1282.98   112.5 1282.25
   127.2  1281.9   146.8  1282.3   170.1 1280.45     181 1279.92   185.1 1279.98
   190.8 1280.86   210.4 1286.93   215.3 1288.77     235 1298.19   249.8 1303.18
   269.5 1309.22   284.3 1314.59   289.2    1316     309 1319.49   318.8 1320.57
   328.7 1321.03   338.6 1320.41   348.4  1319.4   363.2  1317.4   373.1 1316.83
#Mann= 3 , 0 , 0
       0      .1       0   170.1    .045       0   185.1      .1       0
Bank Sta=170.1,185.1
XS Rating Curve= 0 ,0
Exp/Cntr=0.3,0.1

Type RM Length L Ch R = 1 ,2538    ,169.6,167.6,165.7
XS GIS Cut Line= 3
      1772112.39      225992.719     1772288.504      226101.138
     1772376.614      226170.562
#Sta/Elev= 30
       0 1314.06     9.8 1309.65    29.5 1301.55    44.3 1296.87      64 1289.51
    73.9 1286.48    78.8  1285.4    88.6  1284.8    93.6 1283.42   103.4 1280.26
   108.3 1278.87   113.2 1277.78   123.1 1276.32   145.9 1274.04   152.6 1273.23
   157.6  1273.5   160.9 1274.11   177.3  1277.4   182.2 1279.25   187.1 1281.61
     192 1283.61   206.8 1288.38   216.6 1290.95   245.8 1299.21   260.5 1303.06
   265.3 1304.45   275.1 1307.79   284.8 1310.68   294.6 1312.92     319 1317.53
#Mann= 3 , 0 , 0
       0      .1       0   145.9    .045       0   160.9      .1       0
Bank Sta=145.9,160.9
XS Rating Curve= 0 ,0
Exp/Cntr=0.3,0.1

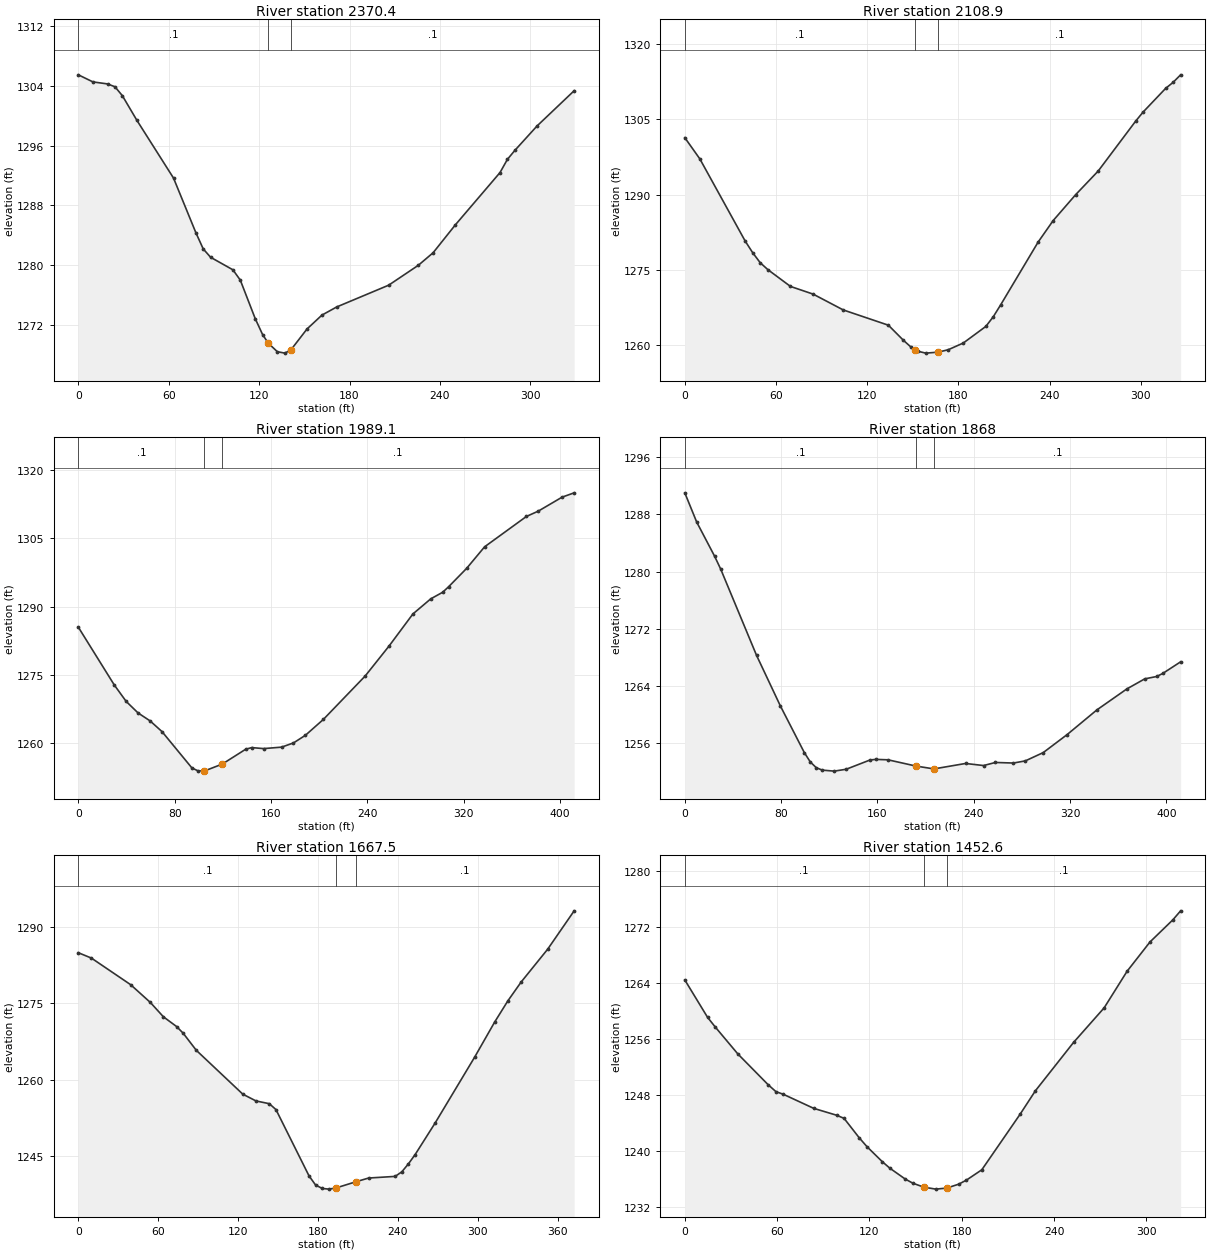
Type RM Length L Ch R = 1 ,2370.4  ,264.5,261.5,258.6
XS GIS Cut Line= 3
     1772017.639      226184.424     1772079.744       226172.68
     1772317.584      226291.547
#Sta/Elev= 30
       0 1305.48     9.7 1304.53    19.4 1304.26    24.3 1303.88    29.2 1302.69
    38.9 1299.37    63.2 1291.63      78 1284.32    82.9 1282.14    87.8 1281.02
   102.6 1279.34   107.5 1277.96   117.4  1272.8   122.3 1270.66   126.1  1269.5
   132.1 1268.36   137.1 1268.17   141.1 1268.61   151.8 1271.41   161.7 1273.27
   171.5 1274.36     206 1277.28   225.7 1279.95   235.5 1281.63   250.3 1285.38
   279.9 1292.38   284.8 1294.15   289.7 1295.34   304.5 1298.63   329.1 1303.35
#Mann= 3 , 0 , 0
       0      .1       0   126.1    .045       0   141.1      .1       0
Bank Sta=126.1,141.1
XS Rating Curve= 0 ,0
Exp/Cntr=0.3,0.1

Type RM Length L Ch R = 1 ,2108.9  ,114.4,119.7,125
XS GIS Cut Line= 3
     1771952.142      226356.646     1772042.791      226441.329
     1772233.729      226507.284
#Sta/Elev= 30
       0 1301.36     9.9 1297.13    39.7 1280.78    44.7 1278.43    49.6 1276.46
    54.6 1275.09    69.5 1271.74    84.4 1270.21   104.2 1267.06   133.9 1264.02
   143.8 1261.01   148.7 1259.68   151.6 1259.16   153.6 1258.81   158.5 1258.46
   166.6 1258.65   173.3 1259.14   183.2 1260.48     198 1263.78   202.9 1265.71
   207.8  1268.1   232.4 1280.58   242.3 1284.86   257.1 1290.02   271.9 1294.72
   296.5 1304.64   301.4 1306.45   316.2 1311.16   321.1 1312.36   326.1 1313.87
#Mann= 3 , 0 , 0
       0      .1       0   151.6    .045       0   166.6      .1       0
Bank Sta=151.6,166.6
XS Rating Curve= 0 ,0
Exp/Cntr=0.3,0.1

Type RM Length L Ch R = 1 ,1989.1  ,126.3,121.1,115.2
XS GIS Cut Line= 3
     1771908.593      226482.301     1772033.475      226563.437
     1772289.302      226623.697
#Sta/Elev= 30
       0 1285.47    29.8 1272.77    39.7 1269.14    49.6 1266.59    59.6 1264.84
    69.5 1262.48    94.3 1254.49    99.3 1253.85   104.2 1253.78   104.6  1253.8
   119.6 1255.34     139  1258.6     144 1258.96   153.9 1258.74   168.8 1259.06
   178.7 1259.99   188.6 1261.67   203.5 1265.16   238.2 1274.71     258  1281.3
   277.9 1288.39   292.7 1291.71   302.6 1293.16   307.6 1294.39   322.5 1298.42
   337.4 1303.16   372.1 1309.84     382 1311.02   401.8  1314.1   411.8 1315.05
#Mann= 3 , 0 , 0
       0      .1       0   104.6    .045       0   119.6      .1       0
Bank Sta=104.6,119.6
XS Rating Curve= 0 ,0
Exp/Cntr=0.3,0.1

Type RM Length L Ch R = 1 ,1868    ,185.1,200.6,216
XS GIS Cut Line= 3
     1771843.553      226540.959     1771953.433      226641.482
     1772195.908      226742.894
#Sta/Elev= 30
       0    1291     9.9 1286.91    24.8 1282.13    29.8 1280.35    59.6 1268.29
    79.4 1261.22    99.3  1254.7   104.2 1253.41   109.2  1252.6   114.2 1252.26
   124.1 1252.12     134 1252.38   153.9 1253.68   158.8 1253.76   168.8  1253.7
   191.9 1252.83   206.9 1252.43   233.2 1253.19   248.1  1252.9     258 1253.33
   272.9 1253.25   282.8 1253.55   297.7 1254.71   317.5 1257.22   342.3 1260.68
   367.1  1263.6     382 1265.01   391.9 1265.34   396.9 1265.76   411.8 1267.39
#Mann= 3 , 0 , 0
       0      .1       0   191.9    .045       0   206.9      .1       0
Bank Sta=191.9,206.9
XS Rating Curve= 0 ,0
Exp/Cntr=0.3,0.1

Type RM Length L Ch R = 1 ,1667.5  ,219.6,214.8,210.1
XS GIS Cut Line= 3
     1771705.197      226639.244     1771783.112      226650.198
     1771924.405      226907.583
#Sta/Elev= 30
       0 1284.91     9.8 1283.86    39.3 1278.63    54.1 1275.14    63.9 1272.32
    73.8 1270.41    78.7 1269.11    88.6 1265.74   123.5 1257.13   133.4  1255.8
   143.4 1255.26   148.4  1254.1   173.2 1241.09   178.2 1239.27   183.2 1238.61
   188.2 1238.48   193.7 1238.73   208.7 1239.95     218 1240.66   237.9 1240.98
   242.9 1241.88   247.9 1243.46   252.9 1245.27   267.8 1251.42   297.6 1264.41
   312.6 1271.29   322.5 1275.45   332.5 1279.16   352.4  1285.6   372.3 1293.14
#Mann= 3 , 0 , 0
       0      .1       0   193.7    .045       0   208.7      .1       0
Bank Sta=193.7,208.7
XS Rating Curve= 0 ,0
Exp/Cntr=0.3,0.1

Type RM Length L Ch R = 1 ,1452.6  ,209.1,191.7,174.6
XS GIS Cut Line= 3
     1771585.355      226802.298     1771671.566      226875.974
     1771806.479      227035.348
#Sta/Elev= 30
       0 1264.46    14.8  1259.1    19.7 1257.74    34.5 1253.85    54.2 1249.44
    59.2 1248.46    64.1 1248.07    83.8 1246.06    98.6 1245.08   103.5 1244.63
   113.4 1241.83   118.4 1240.57   128.3 1238.43   133.3 1237.48   143.2 1235.94
   148.2 1235.34   155.2 1234.78   163.1 1234.49   170.2 1234.64     178  1235.2
     183 1235.78     193 1237.26   217.8 1245.19   227.8 1248.57   252.6  1255.5
   272.5 1260.46   287.4  1265.7   302.3  1269.9   317.2 1273.08   322.2 1274.36
#Mann= 3 , 0 , 0
       0      .1       0   155.2    .045       0   170.2      .1       0
Bank Sta=155.2,170.2
XS Rating Curve= 0 ,0
Exp/Cntr=0.3,0.1

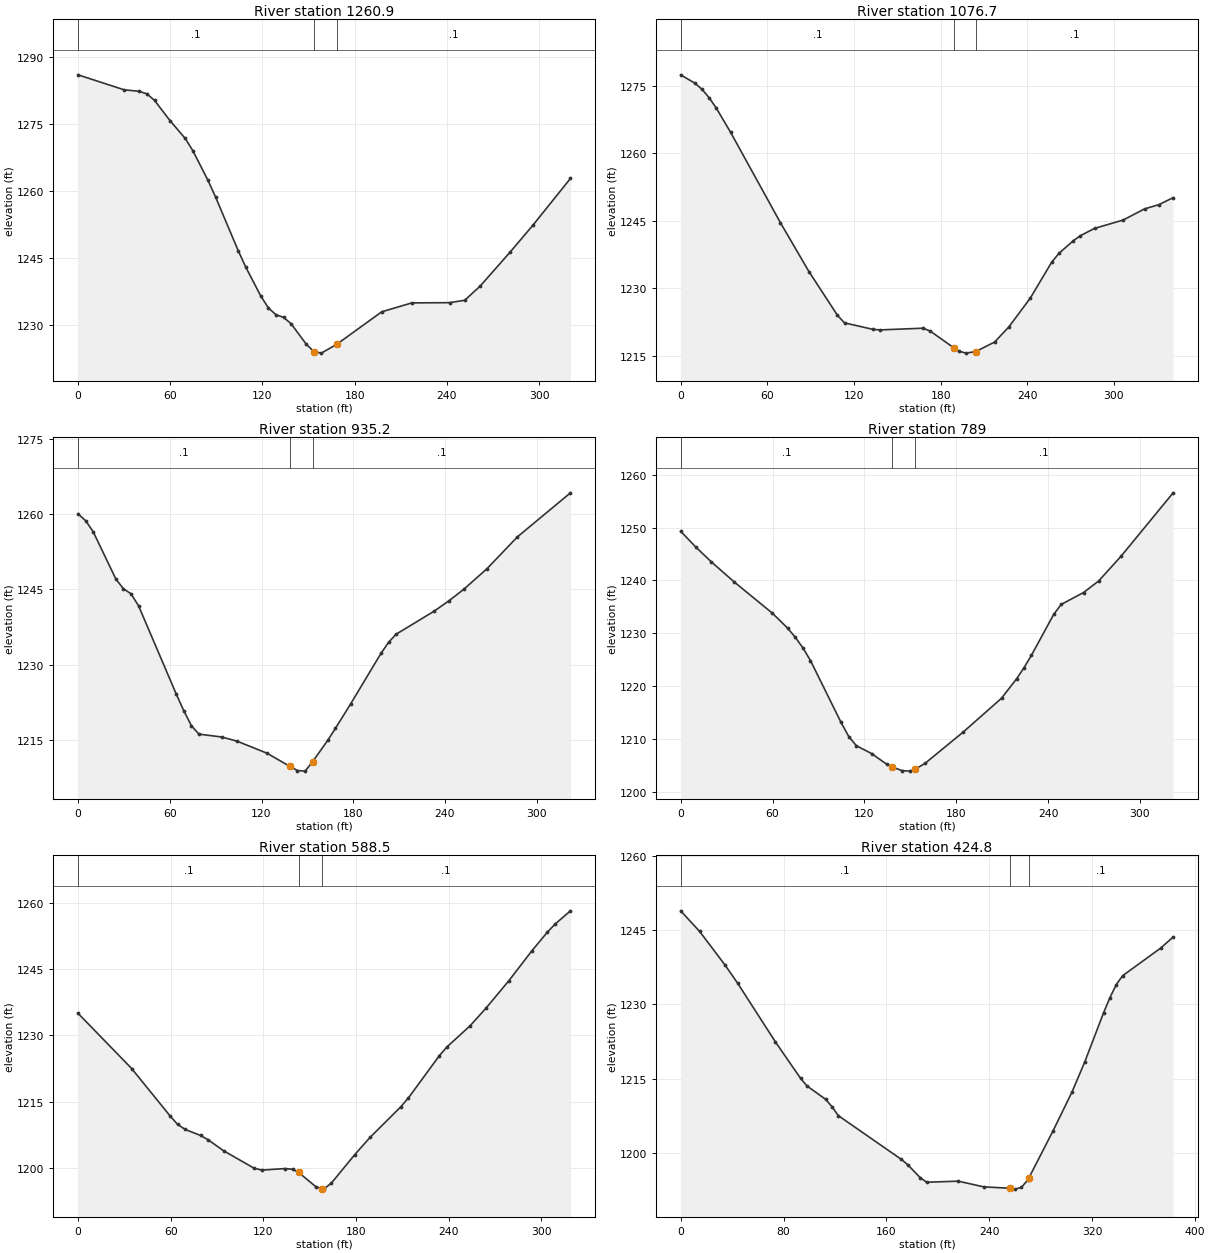
Type RM Length L Ch R = 1 ,1260.9  ,170.8,184.2,197.4
XS GIS Cut Line= 3
      1771469.02      227037.907     1771543.124      227067.143
     1771782.129       227096.26
#Sta/Elev= 30
       0 1285.95    29.9 1282.61    39.8 1282.26    44.8  1281.7    49.8 1280.22
    59.8 1275.73    69.7 1271.74    74.7 1268.99    84.6 1262.33    89.5 1258.62
   104.2 1246.65   109.2 1242.92     119 1236.44   123.9 1233.83   128.8 1232.31
   133.7 1231.74   138.6 1230.32   148.4 1225.78   153.4 1224.09   153.4 1224.08
   158.3 1223.74   168.4 1225.73   197.6 1232.98   217.2 1234.97   241.8 1235.02
   251.6 1235.56   261.5 1238.68   281.1 1246.31   295.9 1252.31   320.4  1262.8
#Mann= 3 , 0 , 0
       0      .1       0   153.4    .045       0   168.4      .1       0
Bank Sta=153.4,168.4
XS Rating Curve= 0 ,0
Exp/Cntr=0.3,0.1

Type RM Length L Ch R = 1 ,1076.7  ,126.9,141.5,156
XS GIS Cut Line= 3
     1771481.772      227081.325     1771517.129      227209.803
     1771677.909      227341.428
#Sta/Elev= 30
       0 1277.49     9.9 1275.62    14.8 1274.26    19.7  1272.4    24.7 1270.08
    34.6 1264.68    69.1 1244.56    88.8  1233.7   108.6 1223.94   113.5 1222.26
   133.2 1220.82   138.2  1220.7   167.9 1221.08   172.8 1220.44   189.3 1216.68
   192.6 1215.97   197.6 1215.53   204.3 1215.87   217.4    1218   227.2 1221.34
   242.1 1227.78   256.9 1235.76   261.9 1237.74   271.8 1240.52   276.7 1241.66
   286.6  1243.3   306.4 1245.16   321.2 1247.64   331.2 1248.59     341 1250.14
#Mann= 3 , 0 , 0
       0      .1       0   189.3    .045       0   204.3      .1       0
Bank Sta=189.3,204.3
XS Rating Curve= 0 ,0
Exp/Cntr=0.3,0.1

Type RM Length L Ch R = 1 ,935.2   ,144.7,146.2,147.7
XS GIS Cut Line= 3
     1771393.992       227144.88     1771423.739      227254.681
      1771474.82      227456.698
#Sta/Elev= 30
       0 1260.05       5 1258.68     9.9 1256.49    24.7 1247.09    29.7 1245.12
    34.6 1244.14    39.6 1241.72    64.3  1224.1    69.2  1220.8    74.2 1217.81
    79.1 1216.16      94 1215.59   103.9 1214.77   123.7 1212.35   138.5 1209.74
   143.5 1208.91   148.5 1208.79   153.5  1210.7   163.4 1214.96   168.3 1217.29
   178.3 1222.18   198.1 1232.23   203.1 1234.44     208 1236.06   232.8 1240.64
   242.8 1242.77   252.7 1245.12   267.6 1249.16   287.4 1255.47   322.1 1264.24
#Mann= 3 , 0 , 0
       0      .1       0   138.5    .045       0   153.5      .1       0
Bank Sta=138.5,153.5
XS Rating Curve= 0 ,0
Exp/Cntr=0.3,0.1

Type RM Length L Ch R = 1 ,789     ,198.6,200.5,202.5
XS GIS Cut Line= 3
     1771263.514      227169.426     1771301.586       227375.56
     1771353.135      227475.057
#Sta/Elev= 30
       0  1249.3      10 1246.28      20 1243.52    34.9 1239.73    59.9  1233.8
    69.9 1230.97    74.9 1229.24    79.9 1227.22    84.8 1224.84   104.8 1213.12
   109.8 1210.47   114.8 1208.72   124.8 1207.23   134.8 1205.18   138.2 1204.69
   144.7 1204.01   149.7 1203.92   153.2 1204.27   159.7  1205.4   184.7 1211.34
   209.6 1217.71   219.4 1221.37   224.2 1223.44   229.1 1225.81   243.7 1233.57
   248.6 1235.46   263.2 1237.71     273 1239.88   287.6 1244.54   321.7 1256.57
#Mann= 3 , 0 , 0
       0      .1       0   138.2    .045       0   153.2      .1       0
Bank Sta=138.2,153.2
XS Rating Curve= 0 ,0
Exp/Cntr=0.3,0.1

Type RM Length L Ch R = 1 ,588.5   ,169.2,163.7,158.2
XS GIS Cut Line= 3
     1771072.007      227214.684      1771093.28      227321.636
     1771114.872      227530.292
#Sta/Elev= 30
       0 1234.96    34.7 1222.47    59.5 1211.78    64.4 1209.84    69.4 1208.68
    79.3 1207.32    84.3 1206.33    94.2 1203.87     114 1199.91     119 1199.49
     134 1199.83     139 1199.67   142.8 1198.96     154 1195.71   157.8  1195.3
     159 1195.18     164 1196.54     179 1202.93     189 1206.87   208.9 1213.79
   213.9 1215.83   233.9 1225.37   238.9 1227.38   253.9 1232.17   263.9 1236.05
   278.9 1242.33   293.8  1249.1   303.8 1253.31   308.8 1255.14   318.8 1258.15
#Mann= 3 , 0 , 0
       0      .1       0   142.8    .045       0   157.8      .1       0
Bank Sta=142.8,157.8
XS Rating Curve= 0 ,0
Exp/Cntr=0.3,0.1

Type RM Length L Ch R = 1 ,424.8   ,149.2,143.1,140.9
XS GIS Cut Line= 3
      1770904.13      227140.696      1770912.97      227297.419
     1770982.268      227512.484
#Sta/Elev= 30
       0 1248.93    14.7 1244.78    34.3 1238.03    44.2 1234.33    73.6 1222.44
    93.2 1215.05    98.1 1213.53   112.8 1210.77   117.7 1209.28   122.6 1207.49
   171.7 1198.62   176.6 1197.55   186.4  1194.9   191.4 1194.02   215.9 1194.23
   235.6 1193.08   255.8  1192.8   260.1 1192.62     265 1192.99     270 1194.51
   270.8 1194.92   289.6 1204.44   304.3 1212.28   314.2 1218.35   328.9 1228.35
   333.8 1231.38   338.7    1234   343.6 1235.79   373.1 1241.37   382.9 1243.62
#Mann= 3 , 0 , 0
       0      .1       0   255.8    .045       0   270.8      .1       0
Bank Sta=255.8,270.8
XS Rating Curve= 0 ,0
Exp/Cntr=0.3,0.1

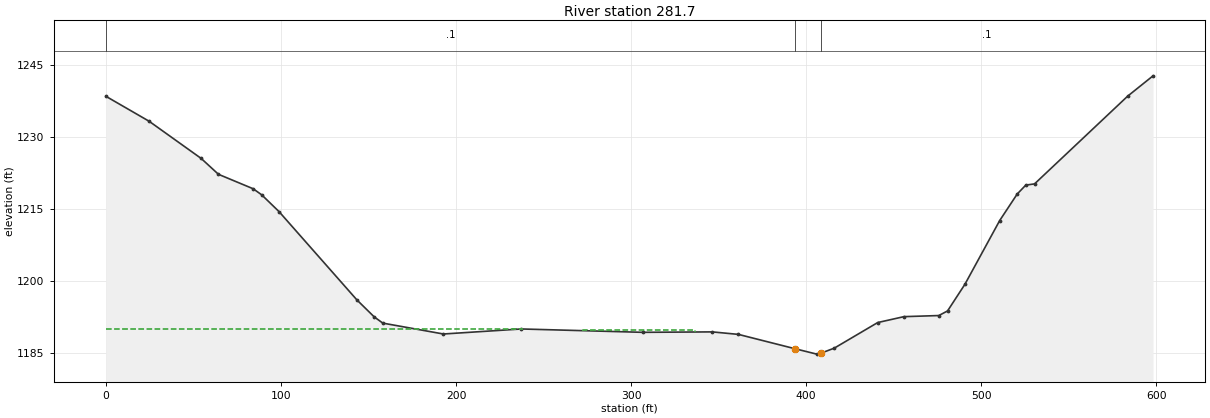
Type RM Length L Ch R = 1 ,281.7   ,278.4,281.7,281.1
XS GIS Cut Line= 4
     1770853.113      227115.306     1770787.598      227414.795
     1770912.111      227600.936     1770977.512      227618.544
#Sta/Elev= 30
       0 1238.48    24.7 1233.27    54.4 1225.52    64.3  1222.2    84.1 1219.19
      89 1217.92    98.9 1214.42   143.4 1195.99   153.3 1192.44   158.2 1191.15
   192.8 1188.88   237.4 1189.93   306.6 1189.23   346.4 1189.32   361.3  1188.8
   393.5 1185.82   406.1 1184.68   408.5 1184.88   416.1 1185.93   440.9 1191.27
   455.9  1192.5   475.8 1192.73   480.8 1193.69   490.7 1199.24   510.6 1212.56
   520.6 1218.09   525.5 1219.95   530.5  1220.2   583.7 1238.51   598.2 1242.75
#Mann= 3 , 0 , 0
       0      .1       0   393.5    .045       0   408.5      .1       0
#XS Ineff= 2 ,-1
       0  238.09 1189.97  272.63   336.4  1189.7
Permanent Ineff=
       F       F
Bank Sta=393.5,408.5
XS Rating Curve= 0 ,0
Exp/Cntr=0.3,0.1

Chan Stop Cuts=-1
Use User Specified Reach Order=0